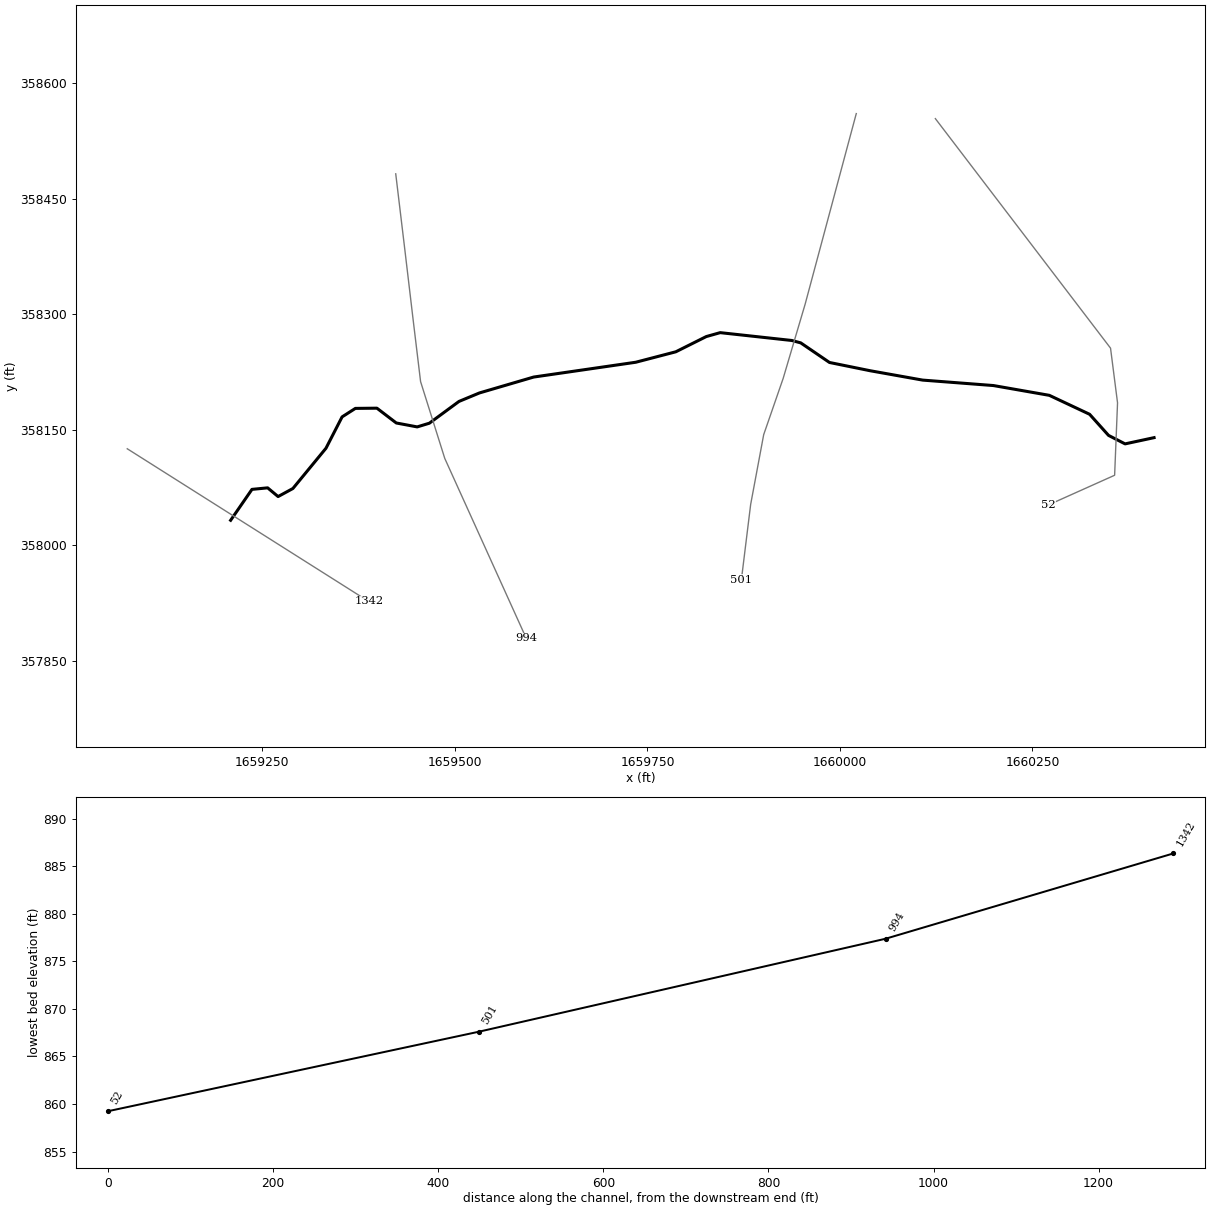
--- ARCHESFKT1.prj (project) ---

Proj Title=ARCHESFKT1
Current Plan=p01
Default Exp/Contr=0.3,0.1
English Units
Geom File=g01
Flow File=f01
Plan File=p01
Y Axis Title=Elevation
X Axis Title(PF)=Main Channel Distance
X Axis Title(XS)=Station
BEGIN DESCRIPTION:
---------- MODELED AS PART OF WVEMD CTP PROGRAM, 2023----------
Stream Name: Arches Fork Tributary 1
Flood Zone:  AFH
Wetzel County, WV
HEC-RAS Version: RAS 6.3
Vertical Datum: NAVD88
Projection: NAD 1983 StatePlane West Virginia S FIPS 4702 (US Feet)
Terrain: 1-meter West Virginia FEMA R3 South Central (collected 2018-2020)
Land Use: 2019 NLCD
Hydrologic Method:
WV 2010 Regional Regression Equations
Additional Model Notes:
None
END DESCRIPTION:
DSS Export Rating Curves= 0
DSS Export Rating Curve Sorted= 0
DSS Export Volume Flow Curves= 0
DXF OffsetX= 0
DXF OffsetY= 0
DXF ScaleX= 1
DXF ScaleY= 10

--- ARCHESFKT1.p01 (plan) ---

Plan Title=Floodplain
Program Version=6.30
Short Identifier=Floodplain
Geom File=g01
Flow File=f01
Subcritical Flow
K Sum by GR= 0
Std Step Tol= 0.01
Critical Tol= 0.01
Num of Std Step Trials= 20
Max Error Tol= 0.3
Flow Tol Ratio= 0.001
Split Flow NTrial= 30
Split Flow Tol= 0.02
Split Flow Ratio= 0.02
Log Output Level= 0
Friction Slope Method= 1
Unsteady Friction Slope Method= 2
Unsteady Bridges Friction Slope Method= 1
Parabolic Critical Depth
Global Vel Dist= 0 , 0 , 0
Global Log Level= 0
CheckData=True
Encroach Param=-1 ,0,0, 0
Computation Interval=1MIN
Output Interval=1HOUR
Instantaneous Interval=1HOUR
Mapping Interval=1HOUR
Computation Time Step Use Courant=        0
Computation Time Step Use Time Series=    0
Computation Time Step Count To Double=0
Computation Time Step Max Doubling=0
Computation Time Step Max Halving=0
Computation Time Step Residence Courant=0
Run HTab= 0
Run UNet= 0
Run Sediment= 0
Run PostProcess= 0
Run WQNet= 0
Run RASMapper=-1
UNET Theta= 1
UNET Theta Warmup= 1
UNET ZTol= 0.02
UNET ZSATol= 0.02
UNET MxIter= 20
UNET Max Iter WO Improvement= 0
UNET MaxInSteps= 0
UNET DtIC= 0
UNET DtMin= 0
UNET MaxCRTS= 20
UNET WFStab= 2
UNET SFStab= 1
UNET WFX= 1
UNET SFX= 1
UNET Gravity=32.17405
UNET 1D Methodology=Finite Difference
UNET DSS MLevel= 4
UNET Pardiso=0
UNET DZMax Abort= 100
UNET Use Existing IB Tables=-1
UNET Froude Reduction=False
UNET Froude Limit= 0.8
UNET Froude Power= 4
UNET D1 Cores= 0
UNET WindReference=Eulerian
UNET WindDragFormulation=Hsu (1988)
UNET D2 Coriolis=0
UNET D2 Cores= 0
UNET D2 Theta= 1
UNET D2 Theta Warmup= 1
UNET D2 Z Tol= 0.01
UNET D2 Volume Tol= 0.01
UNET D2 Max Iterations= 20
UNET D2 Equation= 0
UNET D2 RampUpFraction=0.1
UNET D2 TimeSlices= 1
UNET D2 Turbulence Formulation=None
UNET D2 Eddy Viscosity=0.3
UNET D2 Transverse Eddy Viscosity=0.1
UNET D2 Smagorinsky Mixing=0.05
UNET D2 BCVolumeCheck=0
UNET D2 Cores=0
UNET D2 SolverType=PARDISO (Direct)
UNET D2 Minimum Iterations= 3
UNET D2 Maximum Iterations= 30
UNET D2 Restart Number= 10
UNET D2 Relaxation Coeff=1.3
UNET D2 SOR Precondition Iterations= 10
UNET D2 ILUT Maximum Fill= 8
UNET D2 ILUT Tolerance=1E-08
UNET D2 Convergence Tolerance=0.00001
UNET D1D2 MaxIter= 0
UNET D1D2 ZTol=0.01
UNET D1D2 QTol=0.1
UNET D1D2 MinQTol=1
Write IC File= 0
Write IC File at Fixed DateTime=0
Write IC File at Sim End=0
Echo Input=False
Echo Parameters=False
Echo Output=False
Write Detailed= 0
HDF Write Warmup=0
HDF Write Time Slices=0
HDF Flush=0
HDF Compression= 1
HDF Chunk Size= 1
HDF Spatial Parts= 1
HDF Use Max Rows=0
HDF Fixed Rows= 1
Calibration Method= 0
Calibration Iterations= 20
Calibration Max Change=0.05
Calibration Tolerance=0.2
Calibration Maximum=1.5
Calibration Minimum=0.5
Calibration Optimization Method= 1
WQ AD Non Conservative
WQ ULTIMATE=-1
WQ Max Comp Step=1HOUR
WQ Output Interval=15MIN
WQ Output Selected Increments= 0
WQ Output face flow=0
WQ Output face velocity=0
WQ Output face area=0
WQ Output face dispersion=0
WQ Output cell volume=0
WQ Output cell surface area=0
WQ Output cell continuity=0
WQ Output cumulative cell continuity=0
WQ Output face conc=0
WQ Output face dconc_dx=0
WQ Output face courant=0
WQ Output face peclet=0
WQ Output face adv mass=0
WQ Output face disp mass=0
WQ Output cell mass=0
WQ Output cell source sink temp=0
WQ Output nsm pathways=0
WQ Output nsm derived pathways=0
WQ Create Restart=0
WQ Fixed Restart=0
WQ System Summary=0
WQ Write To DSS=0
Sorting and Armoring Iterations= 10
XS Update Threshold= 0.02
Bed Roughness Predictor= 0
Hydraulics Update Threshold= 0.02
Energy Slope Method= 1
Volume Change Method= 1
Sediment Retention Method= 0
Sediment TS Multiplier= 1
Warm Up Method= 0
XS Weighting Method= 0
Number of US Weighted Cross Sections= 1
Number of DS Weighted Cross Sections= 1
Upstream XS Weight=0
Main XS Weight=1
Downstream XS Weight=0
Number of DS XS's Weighted with US Boundary= 1
Upstream Boundary Weight= 1
Weight of XSs Associated with US Boundary= 0
Number of US XS's Weighted with DS Boundary= 1
Downstream Boundary Weight= 0.5
Weight of XSs Associated with DS Boundary= 0.5
Percentile Method= 0
Sediment Output Level= 3
Mass or Volume Output= 0
Output Increment Type= 1
Profile and TS Output Increment= 1
Transport Output Increment 1
XS Output Flag= 0
XS Output Increment= 10
Read HDF5 Sediment Hotstart= 0
Sediment Hotstart Type= 0
Write Gradation File= 0
Read Gradation Hotstart= 0
Write HDF5 File= 1
Write Binary Output= 1
Write DSS Sediment File= 0
DSS Sediment Output Type= 1
SV Curve= 0
Specific Gage Flag= 0
Subcell Erosion Methods= 0
Subcell Deposition Methods= 0
Advection Scheme= 1
Matrix Solver= 0
Implicit Weighting Factor= 1
Maximum Outer Loop Convergence Iterations= 5
Convergence Maximum Absolute= 0.001
Convergence RMSE= 0.0001
Grain Fractions Max Abs Error= 0.001
Max Subgrid Regions= 1
Max Subgrid Length Scale= 3.402823E+38
Initial Layer Thickness= 3.402823E+38
Min Layer Thickness= 3.402823E+38
Max Layer Thickness= 3.402823E+38
Number of Layers= 5

--- ARCHESFKT1.f01 (steady flow) ---

Flow Title=Flow
Program Version=6.31
Number of Profiles= 1
Profile Names=F01pct
River Rch & RM=ARCHESFKT1,Main,1342
     600
Boundary for River Rch & Prof#=ARCHESFKT1,Main            , 1
Up Type= 0
Dn Type= 3
Dn Slope=0.01903
DSS Import GetInterval= 0
DSS Import GetPeak= 0
DSS Import FillOption= 0

--- ARCHESFKT1.g01 (geometry) ---

Geom Title=Geometry
Program Version=6.30

River Reach=ARCHESFKT1      ,Main
Reach XY= 30
1659208.79431114358032.5795086471659236.49471505358072.716895565
 1659256.8460523358074.6955661481659270.41361047358063.389158309
1659289.63404447358073.8474707311659332.59786931358126.139032811
1659353.51449414358166.8417073041659370.75658564358177.865307316
1659398.73979738358178.1477870641659423.89624314358158.927353054
1659451.03103139358153.8394367251659466.86006796358158.644545227
1659505.30126405358186.9102367311659531.87109281358197.933836728
1659602.25251372358218.5679818091659734.81852156358237.788415805
 1659786.8272758358251.3559739741659826.39937514358271.142023638
1659844.48923397358276.2299399821659937.48347056358266.054107308
1659949.07235813358262.9448615611659986.38297905358237.505936056
1660039.23982872358226.764815807 1660107.3600993358214.610640645
1660199.22376072358207.5440537331660271.86633196358194.824590981
1660324.15789406358170.2334328141660348.74905223358142.815836728
1660370.23096463 358131.792236731660407.87762524358139.884567129

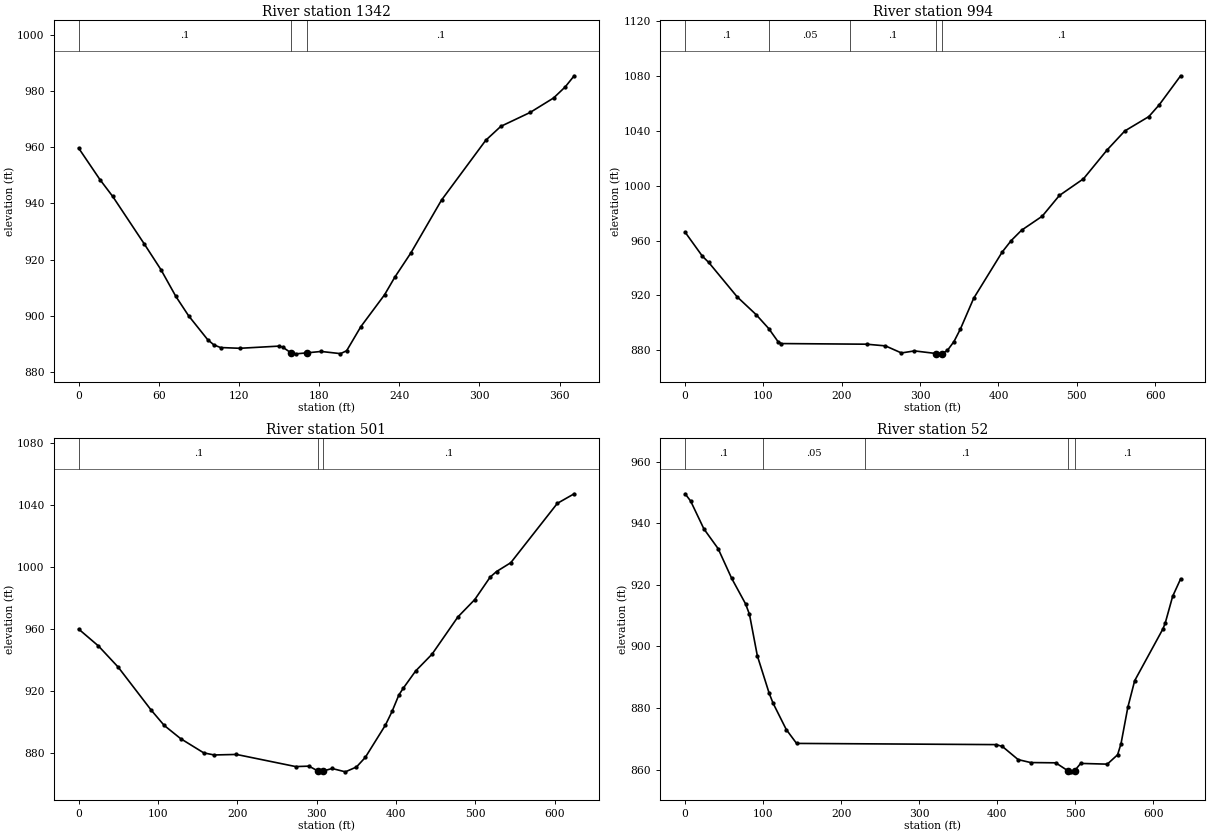
Type RM Length L Ch R = 1 ,1342    ,350.2,348.7,342.4
XS GIS Cut Line= 2
1659074.55790613358125.455790703 1659388.0605453357927.172070201
#Sta/Elev= 30
       0  959.76      16  948.49    25.5  942.52    49.2  925.51    61.6  916.39
    72.8  906.81    82.3  899.93    96.5  891.45   101.2  889.54   106.2  888.59
   120.7  888.32   149.7  889.09   152.6  888.78   158.9   886.7   162.8  886.34
   170.8886.6898   181.5  887.19     196  886.41   200.6  887.44   211.2  896.02
     229  907.43   236.6  913.66   248.7  922.37   271.6   941.2   304.7  962.54
     316  967.52   337.9  972.47   355.5  977.65   364.2   981.6   370.9  985.57
#Mann= 3, -1 ,  0
       0     0.1       0   158.9   0.045       0   170.8     0.1       0
Bank Sta=158.9,170.8
XS Rating Curve= 0 ,0
Exp/Cntr(USF)=0,0
Exp/Cntr=0.3,0.1

Type RM Length L Ch R = 1 ,994     ,494.8,492.5,491.2
XS GIS Cut Line= 6
1659423.16658585358482.4680445941659434.78631325358385.663776249
1659445.68130459358293.6610075091659455.44309609358212.667075008
1659486.86134034 358112.865109251659592.56716567357879.565050915
#Sta/Elev= 30
       0   966.2    22.1  948.63    30.1  944.15    66.4  919.02    90.6  906.03
   106.7  895.86   118.8  886.14   122.8  884.87   231.6  884.41   255.7  883.18
   276.1  878.02   292.8  879.51   320.4 877.609   323.4  877.37   328.3877.6025
   334.8  879.87   343.2  886.34   351.5  895.62   368.3  917.88   404.7  951.66
   416.2  960.04   429.4  967.59   455.8  977.84   477.7  992.97   508.5 1005.16
   538.8 1026.32   561.2 1040.08   591.9 1050.57   605.1 1059.12   632.5 1080.37
#Mann= 5, -1 ,  0
       0     0.1       0   107.5    0.05       0  210.14     0.1       0
   320.4   0.045       0   328.3     0.1       0
Bank Sta=320.4,328.3
XS Rating Curve= 0 ,0
Exp/Cntr(USF)=0,0
Exp/Cntr=0.3,0.1

Type RM Length L Ch R = 1 ,501     ,448,449.4,450.2
XS GIS Cut Line= 6
1660021.18245018358560.6788461661659954.78035201358313.181637749
1659926.26105209358216.8514498321659900.96910793358143.797462091
1659884.03180584358053.0857012571659872.02461201357955.538652256
#Sta/Elev= 30
       0  959.92      25  948.97    49.8  935.34    91.3   907.6   107.8  897.64
   128.5  889.09   157.7  879.86   170.8  878.51   198.9  878.85   273.6     871
   290.3  871.28   301.9868.0786     308868.0909   319.5  869.76   336.2   867.6
   350.2  870.74   361.3  876.92   386.7  897.83   395.1  906.69   403.6  917.26
     409  921.54   424.8  932.82   445.5   943.7     478  967.73   499.3  978.98
   518.7   993.5   526.7  997.09   544.7 1002.82   603.4 1041.19   624.6 1047.38
#Mann= 3, -1 ,  0
       0     0.1       0   301.9   0.045       0     308     0.1       0
Bank Sta=301.9,308
XS Rating Curve= 0 ,0
Exp/Cntr(USF)=0,0
Exp/Cntr=0.3,0.1

Type RM Length L Ch R = 1 ,52      ,,,
XS GIS Cut Line= 5
1660123.87436615358554.1422261781660351.34204938358256.093563779
1660360.43710834358185.0769583711660356.65532809358091.051119835
1660270.31556992358052.347090308
#Sta/Elev= 30
       0  949.63     7.1  947.27    24.1  938.21    42.3  931.81    59.7  922.14
    77.5  913.85    82.5  910.45    92.6  896.96   107.7  884.84   112.7  881.59
   129.7  872.98   142.9  868.48   398.7  868.09   406.7  867.49   426.9  863.22
   442.9  862.26   475.1  862.17   490.7859.5815   495.1  859.24   499.3 859.611
   507.1  861.98   541.2  861.74   554.4  864.79   558.8  868.42   567.5  880.21
   576.3  888.88   612.6  905.75   615.6  907.74     625  916.32   635.2  921.97
#Mann= 5, -1 ,  0
       0     0.1       0     100    0.05       0     230     0.1       0
   490.7   0.045       0   499.3     0.1       0
Bank Sta=490.7,499.3
XS Rating Curve= 0 ,0
Exp/Cntr(USF)=0,0
Exp/Cntr=0.3,0.1
LCMann Table=0

Chan Stop Cuts=-1
Use User Specified Reach Order=0
Composite Channel Slope=5